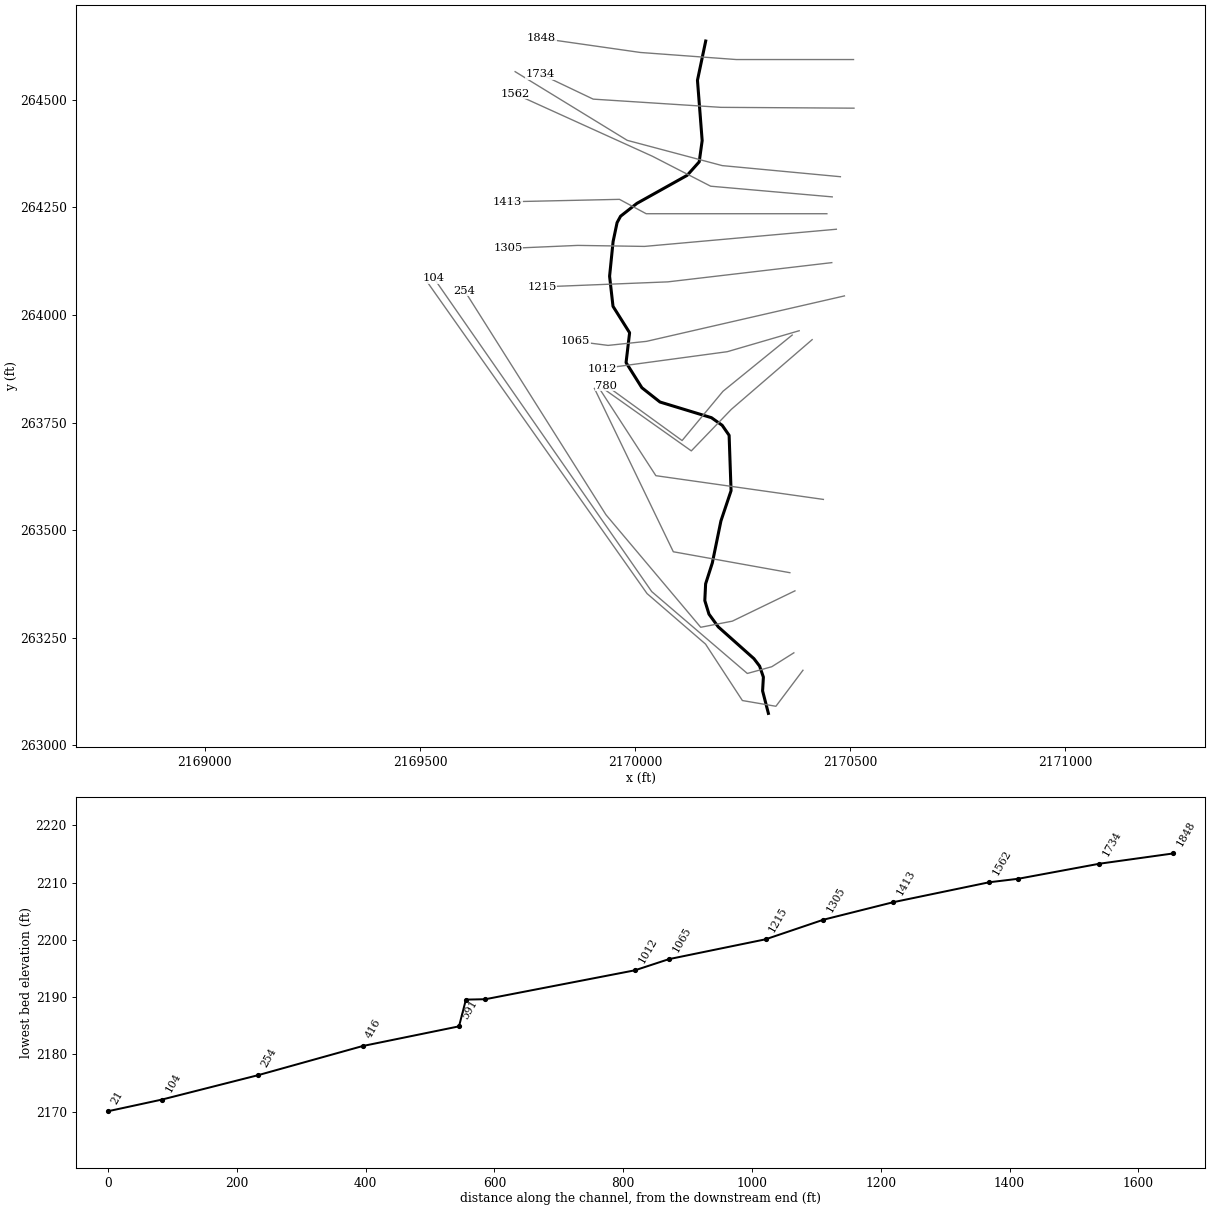
--- TUCKHORNT2.prj (project) ---

Proj Title=TUCKHORNT2
Current Plan=p01
Default Exp/Contr=0,0
English Units
Geom File=g01
Flow File=f01
Plan File=p01
Background Map Layer=DPs_HMS_shifted
Background Map Layer=QC_TUCKHORN
BEGIN DESCRIPTION:
Stream Name- Tuckahoe Run Tributary 2
Flood Zone: Zone A
Greenbrier County, WV
County-Wide Study
WVDHSEM-2018-3, Flood Risk Project
HEC-RAS Version: 5.0.7
General Notes:
For the Hydrology Regression was used.
END DESCRIPTION:
DSS File=dss
DSS Export Rating Curves= 0
DSS Export Rating Curve Sorted= 0
DSS Export Volume Flow Curves= 0
DXF Filename=..\..\H1\MEADOWRV4\MEADOWRV4.
DXF OffsetX= 0
DXF OffsetY= 0
DXF ScaleX= 0
DXF ScaleY= 0

--- TUCKHORNT2.p01 (plan) ---

Plan Title=Floodplain
Program Version=5.07
Short Identifier=Floodplain
Geom File=g01
Flow File=f01
Subcritical Flow
K Sum by GR= 0
Std Step Tol= 0.01
Critical Tol= 0.01
Num of Std Step Trials= 20
Max Error Tol= 0.3
Flow Tol Ratio= 0.001
Split Flow NTrial= 30
Split Flow Tol= 0.02
Split Flow Ratio= 0.02
Log Output Level= 0
Friction Slope Method= 1
Unsteady Friction Slope Method= 2
Unsteady Bridges Friction Slope Method= 1
Parabolic Critical Depth
Global Vel Dist= 0 , 0 , 0
Global Log Level= 0
CheckData=True
Encroach Param=-1 ,0,0, 0
Computation Interval=0.1SEC
Output Interval=1MIN
Instantaneous Interval=Max Profile
Mapping Interval=1HOUR
Computation Time Step Use Courant=        0
Computation Time Step Use Time Series=    0
Computation Time Step Count To Double=0
Computation Time Step Max Doubling=0
Computation Time Step Max Halving=0
Computation Time Step Residence Courant=0
Run HTab= 0
Run UNet= 0
Run Sediment= 0
Run PostProcess= 0
Run WQNet= 0
Run RASMapper= 0
UNET Theta= 0
UNET Theta Warmup= 0
UNET ZTol= 0
UNET ZSATol= 0
UNET MxIter= 0
UNET Max Iter WO Improvement= 0
UNET MaxInSteps= 0
UNET DtIC= 0
UNET DtMin= 0
UNET MaxCRTS= 0
UNET WFStab= 0
UNET SFStab= 0
UNET WFX= 1
UNET SFX= 1
UNET 1D Methodology=Finite Difference
UNET DSS MLevel= 1
UNET Pardiso=0
UNET DZMax Abort= 0
UNET Use Existing IB Tables= 0
UNET Froude Reduction=False
UNET Froude Limit= 0
UNET Froude Power= 0
UNET D1 Cores= 0
UNET D2 Coriolis=0
UNET D2 Cores= 0
UNET D2 Theta= 1
UNET D2 Theta Warmup= 1
UNET D2 Z Tol= 0.01
UNET D2 Volume Tol= 0.01
UNET D2 Max Iterations= 20
UNET D2 Equation= 0
UNET D2 RampUpFraction=0.1
UNET D2 TimeSlices= 1
UNET D2 BCVolumeCheck=0
UNET D1D2 MaxIter= 0
UNET D1D2 ZTol=0.01
UNET D1D2 QTol=0.1
UNET D1D2 MinQTol=1
DSS File=dss
Write IC File= 0
Write IC File at Fixed DateTime=0
Write IC File at Sim End=0
Echo Input=False
Echo Parameters=False
Echo Output=False
Write Detailed= 0
HDF Write Warmup=0
HDF Write Time Slices=0
HDF Flush=0
HDF Face Node Velocities=0
HDF Compression= 1
HDF Chunk Size= 1
HDF Spatial Parts= 1
HDF Use Max Rows=0
HDF Fixed Rows= 1
Calibration Method= 0
Calibration Iterations= 20
Calibration Max Change=0.05
Calibration Tolerance=0.2
Calibration Maximum=1.5
Calibration Minimum=0.5
Calibration Optimization Method= 1
WQ AD Non Conservative
WQ ULTIMATE=-1
WQ Max Comp Step=1HOUR
WQ Output Interval=15MIN
WQ Output Selected Increments= 0
WQ Output face flow=0
WQ Output face velocity=0
WQ Output face area=0
WQ Output face dispersion=0
WQ Output cell volume=0
WQ Output cell surface area=0
WQ Output cell continuity=0
WQ Output cumulative cell continuity=0
WQ Output face conc=0
WQ Output face dconc_dx=0
WQ Output face courant=0
WQ Output face peclet=0
WQ Output face adv mass=0
WQ Output face disp mass=0
WQ Output cell mass=0
WQ Output cell source sink temp=0
WQ Output nsm pathways=0
WQ Output nsm derived pathways=0
WQ Output MaxMinRange=-1
WQ Daily Max Min Mean=-1
WQ Daily Range=0
WQ Daily Time=0
WQ Create Restart=0
WQ Fixed Restart=0
WQ System Summary=0
WQ Write To DSS=0
WQ Use Fixed Temperature=0
Sorting and Armoring Iterations= 10
XS Update Threshold= 0.02
Bed Roughness Predictor= 0
Hydraulics Update Threshold= 0.02
Energy Slope Method= 1
Volume Change Method= 1
Sediment Retention Method= 0
XS Weighting Method= 0
Number of US Weighted Cross Sections= 1
Number of DS Weighted Cross Sections= 1
Upstream XS Weight=0
Main XS Weight=1
Downstream XS Weight=0
Number of DS XS's Weighted with US Boundary= 1
Upstream Boundary Weight= 1
Weight of XSs Associated with US Boundary= 0
Number of US XS's Weighted with DS Boundary= 1
Downstream Boundary Weight= 0.5
Weight of XSs Associated with DS Boundary= 0.5
Percentile Method= 0
Sediment Output Level= 3
Mass or Volume Output= 0
Output Increment Type= 1
Profile and TS Output Increment= 1
XS Output Flag= 0
XS Output Increment= 10
Write Gradation File= 0
Read Gradation Hotstart= 0
Write HDF5 File= 1
Write Binary Output= 1
Write DSS Sediment File= 0
SV Curve= 0
Specific Gage Flag= 0

--- TUCKHORNT2.f01 (steady flow) ---

Flow Title=MasterFlow
Program Version=5.07
Number of Profiles= 6
Profile Names=f1p,f10p,f4p,f2p,f02p,f1pplus
River Rch & RM=BROADRN,Main            ,3339
     761     339     488     619    1150     917
River Rch & RM=LAURELBR,Main            ,3440
     558     218     334     440     888     691
River Rch & RM=LAURELCK1,Main            ,8407
     526     277     369     445     736     778
River Rch & RM=LAURELCK1,Main            ,7622
     821     440     581     697    1140    1210
River Rch & RM=LAURELCK1,Main            ,6012
     949     512     674     807    1310    1400
River Rch & RM=LAURELCK1,Main            ,2069
    1180     639     838    1000    1620    1740
River Rch & RM=MLGNCK,Main            ,43088
    1400     765    1000    1190    1920    2070
River Rch & RM=MLGNCK,Main            ,41997
    1560     858    1120    1330    2140    2310
River Rch & RM=MLGNCK,Main            ,35646
    1910    1060    1370    1630    2610    2820
River Rch & RM=MLGNCK,Main            ,34400
    2210    1230    1600    1890    3010    3270
River Rch & RM=MLGNCK,Main            ,29681
    3770    2150    2750    3250    5090    5580
River Rch & RM=MLGNCK,Main            ,25204
    4210    2400    3080    3630    5670    6230
River Rch & RM=MLGNCK,Main            ,13347
    4770    2730    3490    4110    6400    7050
River Rch & RM=MLGNCKTR3,Main            ,13516
    1790     990    1290    1530    2450    2650
River Rch & RM=MLGNCKTR3,Main            ,9632
    2060    1140    1480    1760    2810    3040
River Rch & RM=MLGNCKTR4,Main            ,3322
     500     263     350     423     700     739
River Rch & RM=MLGNCKTR4,Main            ,2737
     557     294     391     471     778     823
River Rch & RM=TUCKHORN,Main            ,14873
     566     299     398     479     791     837
River Rch & RM=TUCKHORN,Main            ,12657
     639     339     450     542     891     945
River Rch & RM=TUCKHORN,Main            ,10275
    1150     622     817     976    1580    1700
River Rch & RM=TUCKHORN,Main            ,6291
    1390     758     991    1180    1900    2050
River Rch & RM=TUCKHORN,Main            ,4342
    1770     980    1280    1520    2430    2620
River Rch & RM=TUCKHORN,Main            ,346
    2140    1190    1540    1830    2910    3160
River Rch & RM=TUCKHORN,Main            ,239
    3116    1352    1964    2514    3780    4764
River Rch & RM=TUCKHORNT2,Main            ,1848
     570     301     400     482     796     842
Boundary for River Rch & Prof#=BROADRN,Main            , 1
Up Type= 0
Dn Type= 3
Dn Slope=0.05922
Boundary for River Rch & Prof#=BROADRN,Main            , 2
Up Type= 0
Dn Type= 3
Dn Slope=0.05922
Boundary for River Rch & Prof#=BROADRN,Main            , 3
Up Type= 0
Dn Type= 3
Dn Slope=0.05922
Boundary for River Rch & Prof#=BROADRN,Main            , 4
Up Type= 0
Dn Type= 3
Dn Slope=0.05922
Boundary for River Rch & Prof#=BROADRN,Main            , 5
Up Type= 0
Dn Type= 3
Dn Slope=0.05922
Boundary for River Rch & Prof#=BROADRN,Main            , 6
Up Type= 0
Dn Type= 3
Dn Slope=0.05922
Boundary for River Rch & Prof#=LAURELBR,Main            , 1
Up Type= 0
Dn Type= 3
Dn Slope=0.04145
Boundary for River Rch & Prof#=LAURELBR,Main            , 2
Up Type= 0
Dn Type= 3
Dn Slope=0.04145
Boundary for River Rch & Prof#=LAURELBR,Main            , 3
Up Type= 0
Dn Type= 3
Dn Slope=0.04145
Boundary for River Rch & Prof#=LAURELBR,Main            , 4
Up Type= 0
Dn Type= 3
Dn Slope=0.04145
Boundary for River Rch & Prof#=LAURELBR,Main            , 5
Up Type= 0
Dn Type= 3
Dn Slope=0.04145
Boundary for River Rch & Prof#=LAURELBR,Main            , 6
Up Type= 0
Dn Type= 3
Dn Slope=0.04145
Boundary for River Rch & Prof#=LAURELCK1,Main            , 1
Up Type= 0
Dn Type= 3
Dn Slope=0.009
Boundary for River Rch & Prof#=LAURELCK1,Main            , 2
Up Type= 0
Dn Type= 3
Dn Slope=0.009
Boundary for River Rch & Prof#=LAURELCK1,Main            , 3
Up Type= 0
Dn Type= 3
Dn Slope=0.009
Boundary for River Rch & Prof#=LAURELCK1,Main            , 4
Up Type= 0
Dn Type= 3
Dn Slope=0.009
Boundary for River Rch & Prof#=LAURELCK1,Main            , 5
Up Type= 0
Dn Type= 3
Dn Slope=0.009
Boundary for River Rch & Prof#=LAURELCK1,Main            , 6
Up Type= 0
Dn Type= 3
Dn Slope=0.009
Boundary for River Rch & Prof#=MLGNCK,Main            , 1
Up Type= 0
Dn Type= 3
Dn Slope=0.0302
Boundary for River Rch & Prof#=MLGNCK,Main            , 2
Up Type= 0
Dn Type= 3
Dn Slope=0.0302
Boundary for River Rch & Prof#=MLGNCK,Main            , 3
Up Type= 0
Dn Type= 3
Dn Slope=0.0302
Boundary for River Rch & Prof#=MLGNCK,Main            , 4
Up Type= 0
Dn Type= 3
Dn Slope=0.0302
Boundary for River Rch & Prof#=MLGNCK,Main            , 5
Up Type= 0
Dn Type= 3
Dn Slope=0.0302
Boundary for River Rch & Prof#=MLGNCK,Main            , 6
Up Type= 0
Dn Type= 3
Dn Slope=0.0302
Boundary for River Rch & Prof#=MLGNCKTR3,Main            , 1
Up Type= 0
Dn Type= 3
Dn Slope=0.00395
Boundary for River Rch & Prof#=MLGNCKTR3,Main            , 2
Up Type= 0
Dn Type= 3
Dn Slope=0.00395
Boundary for River Rch & Prof#=MLGNCKTR3,Main            , 3
Up Type= 0
Dn Type= 3
Dn Slope=0.00395
Boundary for River Rch & Prof#=MLGNCKTR3,Main            , 4
Up Type= 0
Dn Type= 3
Dn Slope=0.00395
Boundary for River Rch & Prof#=MLGNCKTR3,Main            , 5
Up Type= 0
Dn Type= 3
Dn Slope=0.00395
Boundary for River Rch & Prof#=MLGNCKTR3,Main            , 6
Up Type= 0
Dn Type= 3
Dn Slope=0.00395
Boundary for River Rch & Prof#=MLGNCKTR4,Main            , 1
Up Type= 0
Dn Type= 3
Dn Slope=0.01609
Boundary for River Rch & Prof#=MLGNCKTR4,Main            , 2
Up Type= 0
Dn Type= 3
Dn Slope=0.01609
Boundary for River Rch & Prof#=MLGNCKTR4,Main            , 3
Up Type= 0
Dn Type= 3
Dn Slope=0.01609
Boundary for River Rch & Prof#=MLGNCKTR4,Main            , 4
Up Type= 0
Dn Type= 3
Dn Slope=0.01609
Boundary for River Rch & Prof#=MLGNCKTR4,Main            , 5
Up Type= 0
Dn Type= 3
Dn Slope=0.01609
Boundary for River Rch & Prof#=MLGNCKTR4,Main            , 6
Up Type= 0
Dn Type= 3
Dn Slope=0.01609
Boundary for River Rch & Prof#=TUCKHORN,Main            , 1
Up Type= 0
Dn Type= 1
Dn Known WS=2122.5
Boundary for River Rch & Prof#=TUCKHORN,Main            , 2
Up Type= 0
Dn Type= 1
Dn Known WS=2120.48
Boundary for River Rch & Prof#=TUCKHORN,Main            , 3
Up Type= 0
Dn Type= 1
Dn Known WS=2121.09
Boundary for River Rch & Prof#=TUCKHORN,Main            , 4
Up Type= 0
Dn Type= 1
Dn Known WS=2121.64
Boundary for River Rch & Prof#=TUCKHORN,Main            , 5
Up Type= 0
Dn Type= 1
Dn Known WS=2123.27
Boundary for River Rch & Prof#=TUCKHORN,Main            , 6
Up Type= 0
Dn Type= 1
Dn Known WS=2124.99
Boundary for River Rch & Prof#=TUCKHORNT2,Main            , 1
Up Type= 0
Dn Type= 3
Dn Slope=0.02818
Boundary for River Rch & Prof#=TUCKHORNT2,Main            , 2
Up Type= 0
Dn Type= 3
Dn Slope=0.02818
Boundary for River Rch & Prof#=TUCKHORNT2,Main            , 3
Up Type= 0
Dn Type= 3
Dn Slope=0.02818
Boundary for River Rch & Prof#=TUCKHORNT2,Main            , 4
Up Type= 0
Dn Type= 3
Dn Slope=0.02818
Boundary for River Rch & Prof#=TUCKHORNT2,Main            , 5
Up Type= 0
Dn Type= 3
Dn Slope=0.02818
Boundary for River Rch & Prof#=TUCKHORNT2,Main            , 6
Up Type= 0
Dn Type= 3
Dn Slope=0.02818
DSS Import GetInterval= 0
DSS Import GetPeak= 0
DSS Import FillOption= 0

--- TUCKHORNT2.g01 (geometry) ---

Geom Title=MasterGeometry
Program Version=5.07

River Reach=TUCKHORNT2      ,Main
Reach XY= 30
     2170164.464      264637.065     2170145.289      264545.752
     2170156.231      264405.542     2170149.351      264356.086
     2170121.433      264324.827     2170004.476      264259.522
     2169966.495      264229.665     2169958.368       264214.79
     2169949.111      264170.721     2169940.966      264090.229
     2169948.905      264020.152     2169987.513      263958.692
     2169979.261      263889.349     2170015.998        263830.9
     2170058.137      263797.639      2170177.82      263761.197
     2170202.783      263743.489     2170218.895      263720.241
     2170223.419      263591.429     2170199.841      263521.096
     2170179.833      263423.405     2170164.263      263374.882
     2170162.364      263336.022      2170172.06      263304.407
     2170193.584      263274.871      2170276.59      263200.892
     2170289.794      263183.578     2170298.575      263157.991
     2170296.749      263125.913     2170310.218      263073.668

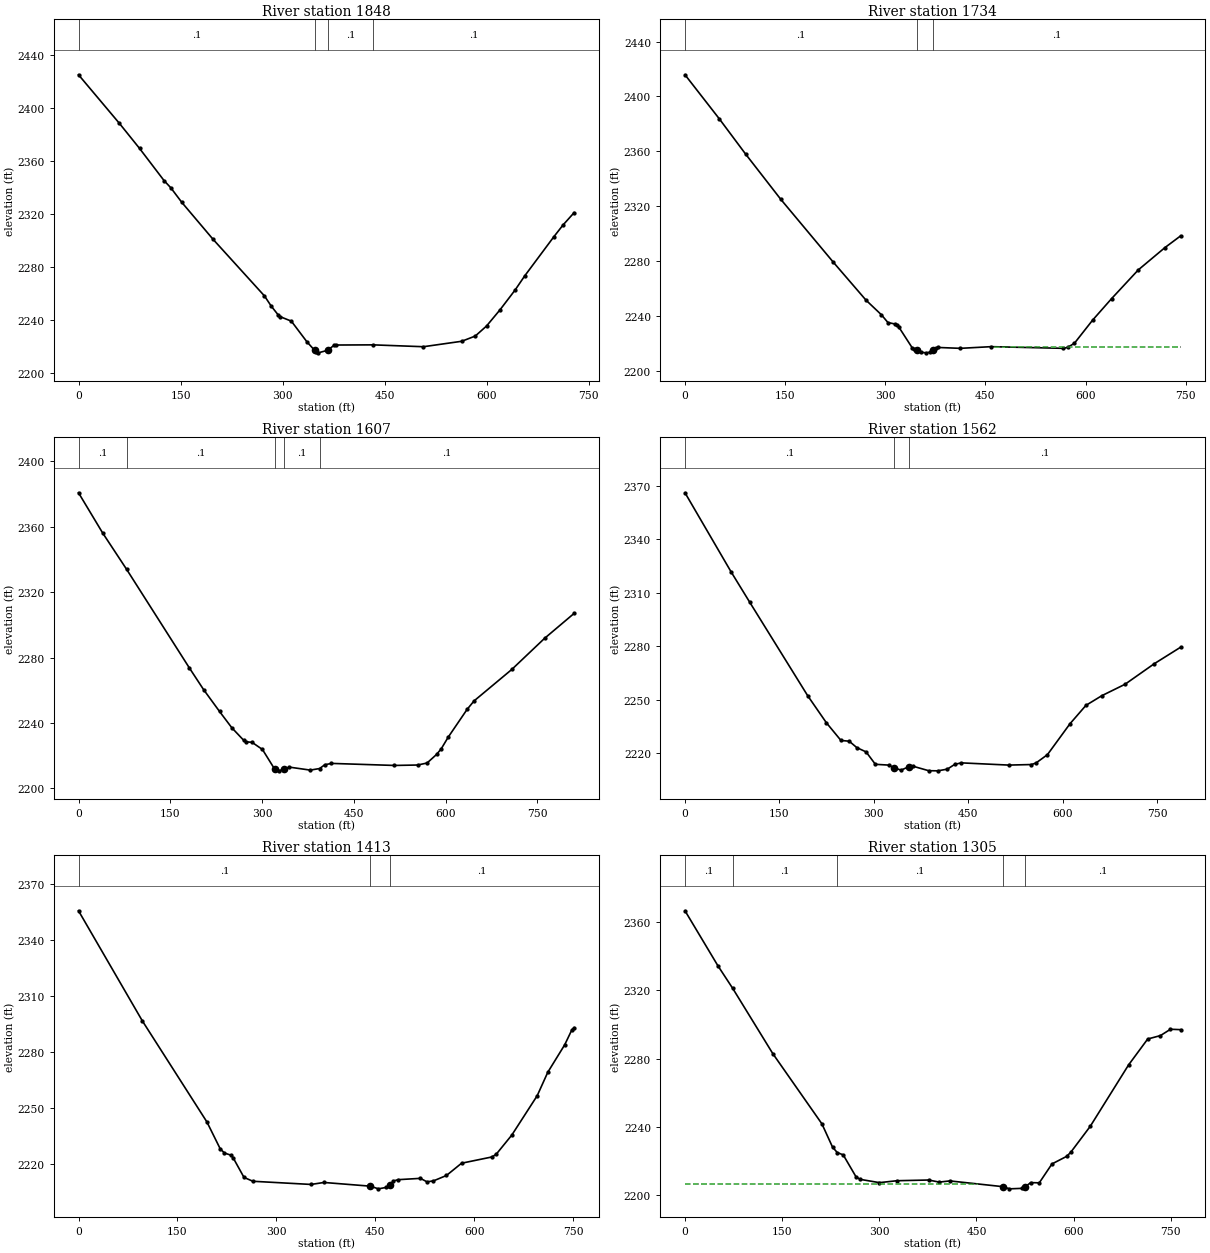
Type RM Length L Ch R = 1 ,1848    ,114.9,114.9,114.9
XS GIS Cut Line= 4
2170508.16732546264593.9825163412170235.71973174264593.982516341
2170012.59454722 264610.423319412169782.42330425264643.304925549
#Sta/Elev= 30
       0 2425.02    60.2 2388.28    89.7 2369.45   125.8 2345.11   135.6 2339.76
     152 2328.61   197.9 2300.76   273.4 2258.05   283.3 2250.39   293.1 2244.03
   296.4  2242.4   312.9 2239.02   335.9 2223.36  347.092217.008   349.1 2215.75
   352.4 2215.09   366.3 2217.01   375.4 2220.68   378.7 2220.99  433.232221.112
   507.1 2219.71   563.4 2223.82   583.3 2227.76   599.9 2235.35   619.7 2247.57
   641.9 2262.53   656.2 2273.32   698.8  2302.7   712.5  2311.7728.6857 2320.96
#Mann= 4 ,-1 , 0
       0      .1       0  347.09    .045       0   366.3      .1       0
  433.23      .1       0
#XS Ineff= 2 , 0
                          392.23         2220.91
Permanent Ineff=
       F       F
Bank Sta=347.09,366.3
XS Rating Curve= 0 ,0
Exp/Cntr(USF)=0,0
Exp/Cntr=0.3,0.1

Type RM Length L Ch R = 1 ,1734    ,126.2,126.2,126.2
XS GIS Cut Line= 4
2170509.27374873264480.9255227012170199.85253277264482.835530207
2169902.84636559264501.9356052662169780.60588521264560.190834197
#Sta/Elev= 30
       0 2415.82    51.4 2383.73    90.8 2358.06   143.3 2325.22     222 2279.41
   271.2 2251.64   294.2 2241.03     304 2235.36   313.9 2234.36   317.2 2233.57
   320.5 2231.94   340.2 2217.08   343.5  2215.8   347.6  2215.1   353.4  2213.7
   361.5 2213.29   366.5 2213.65   372.2 2215.31   376.4 2216.86   379.7 2217.19
   412.5 2216.57   458.6 2217.79     567 2216.58   573.6 2217.33   583.5 2220.34
   610.7 2237.15   639.1  2252.8   679.1 2273.72     719 2289.95   742.5 2298.49
#Mann= 3 , 0 , 0
       0      .1       0   347.6    .045       0   372.2      .1       0
#XS Ineff= 2 , 0
                          463.37         2217.81
Permanent Ineff=
       F       F
Bank Sta=347.6,372.2
XS Rating Curve= 0 ,0
Exp/Cntr(USF)=0,0
Exp/Cntr=0.3,0.1

Type RM Length L Ch R = 1 ,1607    ,45.1,45.1,45.1
XS GIS Cut Line= 4
2170477.63440547264321.534922618 2170202.8381256264347.370470299
2169982.06162724264406.0876241182169721.35746428264565.798282507
#Sta/Elev= 30
       0 2380.79    39.6 2356.12   78.592333.976   181.3 2273.57   204.4  2260.4
   230.5    2247   250.5 2237.06   270.3 2229.23   273.6 2228.45   283.7  2228.1
   300.7 2223.72   320.42211.845   327.9 2210.66   335.1 2211.71   344.8 2212.92
   378.8 2211.11  394.15 2212.07   402.5 2214.37   413.5 2215.21   516.3 2213.96
   554.4 2214.22   569.8 2215.45   585.2 2220.66   592.9 2224.12   604.3 2231.25
   635.3 2248.31   646.7 2253.48   708.3  2272.7   761.8 2291.71810.1948 2307.01
#Mann= 5 ,-1 , 0
       0      .1       0   78.59      .1       0   320.4    .045       0
   335.1      .1       0  394.15      .1       0
Bank Sta=320.4,335.1
XS Rating Curve= 0 ,0
Exp/Cntr(USF)=0,0
Exp/Cntr=0.3,0.1

Type RM Length L Ch R = 1 ,1562    ,148.9,148.9,148.9
XS GIS Cut Line= 4
2170458.65854982264274.6447120612170175.97743894264299.474809638
2170040.36690602264369.1900836042169720.44064878264514.350654055
#Sta/Elev= 30
       0 2366.24    73.3 2321.78   102.9 2304.73   195.1 2252.17   224.6 2237.09
   247.8 2227.12     261 2226.69     273  2223.1   287.8 2220.68   302.5 2213.72
   323.9 2213.27     332 2211.81   343.4 2210.44   355.5 2212.36   362.8 2212.59
   387.2 2210.13   401.8 2210.05   416.9 2211.01   428.6 2213.68   438.9 2214.53
   514.6 2213.28   550.6 2213.59   557.8 2214.47   575.9 2219.12   611.8 2236.51
   637.1 2246.82   662.3 2252.25   699.3 2258.69   745.7 2270.22   787.6  2279.5
#Mann= 3 , 0 , 0
       0      .1       0     332    .045       0   355.5      .1       0
Bank Sta=332,355.5
XS Rating Curve= 0 ,0
Exp/Cntr(USF)=0,0
Exp/Cntr=0.3,0.1

Type RM Length L Ch R = 1 ,1413    ,108.5,108.5,108.5
XS GIS Cut Line= 4
2170446.24350103264235.4895581892170026.04184973264235.489558189
2169963.96660578264268.9146895432169703.25058122264263.184667025
#Sta/Elev= 30
       0 2355.83    96.7 2296.77   194.7 2242.47   214.8 2228.09   221.3 2225.78
   231.2 2224.64   234.5 2223.21   250.9 2212.72   264.4 2210.63   352.6 2208.93
   372.2 2209.99   442.6    2208   454.7 2206.57   466.8 2207.35   471.7 2208.45
   477.5  2210.8     485  2211.5   518.5  2212.2   528.3 2210.33   538.2 2210.84
   557.9 2213.74   580.8 2220.32   626.8 2223.68   633.3 2225.12     657 2235.44
   695.5 2256.57   711.5 2269.12   737.2  2283.9   748.2 2292.03   751.5 2293.07
#Mann= 3 , 0 , 0
       0      .1       0   442.6    .045       0   471.7      .1       0
#XS Ineff= 2 , 0
          372.25 2209.98
Permanent Ineff=
       F       F
Bank Sta=442.6,471.7
XS Rating Curve= 0 ,0
Exp/Cntr(USF)=0,0
Exp/Cntr=0.3,0.1

Type RM Length L Ch R = 1 ,1305    ,89.8,89.8,89.8
XS GIS Cut Line= 4
2170468.23966086264199.4032426732170021.98929183264159.475578076
2169866.97600575264161.8242642292169704.91666121264154.778205771
#Sta/Elev= 30
       0 2366.79    50.8  2334.5   73.782321.157   135.6 2282.89   211.4 2241.67
   227.8 2228.01  235.062224.824   244.3 2223.45   264.2 2210.49   270.6 2209.07
   300.2 2207.15   327.4 2208.28   376.1 2208.69   392.5 2207.47     409 2208.16
  491.292204.766     501 2203.51   520.7  2203.8  525.392204.766   533.8 2207.17
     547 2207.03   566.6 2218.13   589.6 2222.64   596.2 2225.27   625.7 2240.21
   684.8 2276.22   714.4 2291.49   734.1  2293.5   749.6 2297.22765.2766 2296.99
#Mann= 5 ,-1 , 0
       0      .1       0   73.78      .1       0  235.06      .1       0
  491.29    .045       0  525.39      .1       0
#XS Ineff= 2 , 0
          452.01 2206.64
Permanent Ineff=
       F       F
Bank Sta=491.29,525.39
XS Rating Curve= 0 ,0
Exp/Cntr(USF)=0,0
Exp/Cntr=0.3,0.1

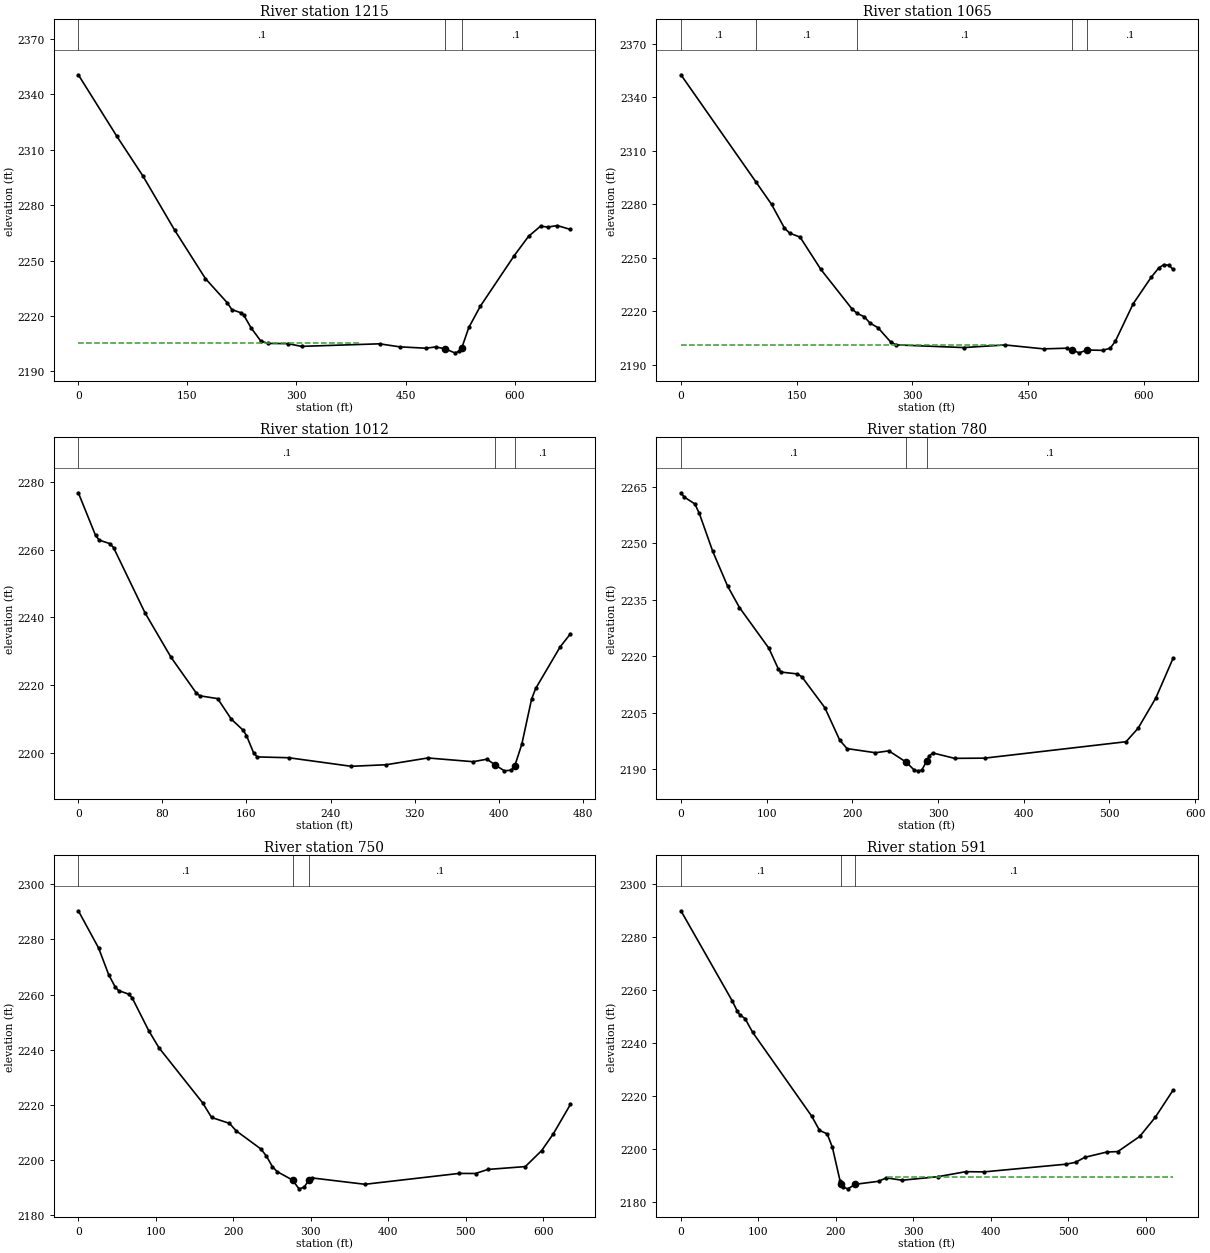
Type RM Length L Ch R = 1 ,1215    ,150.2,150.2,150.2
XS GIS Cut Line= 3
2170457.60439156264121.756559799 2170076.4055062264077.034902857
2169783.58513337264065.322087944
#Sta/Elev= 30
       0  2350.5    52.6 2317.45    88.9  2295.7   132.7 2266.32   174.8 2240.25
   204.6 2227.28   211.2 2223.49   224.4 2221.64   227.7 2220.38   237.6 2213.59
   250.8 2206.57   260.7 2205.19   287.9 2205.07     307 2203.59   414.3 2204.97
     442 2203.33   478.2  2202.6   491.3 2203.28   504.4  2202.3   517.6 2200.09
   524.1 2200.83   527.1 2202.44   537.1 2213.82   552.9  2225.3   599.6  2252.7
   619.3 2263.13   635.8 2268.62   645.6 2268.11   658.7 2268.94   676.9 2266.83
#Mann= 3 , 0 , 0
       0      .1       0   504.4    .045       0   527.1      .1       0
#XS Ineff= 2 , 0
          386.64 2205.37
Permanent Ineff=
       F       F
Bank Sta=504.4,527.1
XS Rating Curve= 0 ,0
Exp/Cntr(USF)=0,0
Exp/Cntr=0.3,0.1

Type RM Length L Ch R = 1 ,1065    ,52.6,52.6,52.6
XS GIS Cut Line= 4
2170487.02915008 264044.389956592170026.68666414263938.699079715
2169937.43659033263929.3043351042169861.98715923263938.990553932
#Sta/Elev= 30
       02352.656  97.2572292.527 117.4542279.987 134.2852266.591 141.0172263.783
 154.4822261.575 181.4122243.455 221.806 2221.28 228.5382218.719 237.5432216.948
 245.3692213.249 255.468 2210.76 272.2992202.561 279.0312201.086 366.5522199.586
 420.411 2201.05 470.243 2198.85 500.6232199.232  507.082198.241  516.262196.624
   526.82198.221 546.8092198.018 556.7052199.257 563.3072203.146 586.4612224.191
 609.6152238.932 619.539 2244.24 626.1542246.125  632.77 2245.74 638.1312243.484
#Mann= 5 ,-1 , 0
       0      .1       0  97.257      .1       0 228.538      .1       0
  507.08    .045       0   526.8      .1       0
#XS Ineff= 2 , 0
          420.18 2201.24
Permanent Ineff=
       F       F
Bank Sta=507.08,526.8
XS Rating Curve= 0 ,0
Exp/Cntr(USF)=0,0
Exp/Cntr=0.3,0.1

Type RM Length L Ch R = 1 ,1012    ,232.3,232.3,232.3
XS GIS Cut Line= 3
2170381.78357369263963.4140175522170214.69611707263914.680176038
2169923.06662103263875.228971003
#Sta/Elev= 30
       0 2276.77    16.4 2264.17    19.9  2262.8    30.1 2261.75    33.5 2260.59
    63.5  2241.3    88.2  2228.2   112.1 2217.71   115.6 2216.83   132.6    2216
   145.5 2209.96   156.6 2206.74     160  2205.1   166.8 2199.98   170.2 2198.79
   200.2 2198.55   259.7 2196.02   292.9 2196.48   332.6 2198.48   375.6 2197.38
   388.9 2198.12   396.3 2196.48   405.4 2194.68     412 2194.88   415.4 2196.24
     422 2202.54   431.3 2215.86   435.2    2219   458.4 2231.23   468.3 2235.15
#Mann= 3 , 0 , 0
       0      .1       0   396.3    .045       0   415.4      .1       0
Bank Sta=396.3,415.4
XS Rating Curve= 0 ,0
Exp/Cntr(USF)=0,0
Exp/Cntr=0.5,0.3

Type RM Length L Ch R = 1 ,780     ,30.3,30.3,30.3
XS GIS Cut Line= 4
2170365.53895985263953.3578280332170204.63992755 263822.62736429
2170109.53081428263708.042393178 2169932.9857787 263836.01780234
#Sta/Elev= 30
       02263.342   3.6442262.246  16.3252260.372  21.4882257.856  37.0962247.827
  54.3712238.646  68.3132232.918 102.6022222.141 113.552  2216.7 116.5952215.815
 135.949 2215.32 141.1512214.547 167.9052206.383 185.4162197.719  193.872195.527
 226.9352194.429 242.6322194.922 262.8942191.929 272.4782189.777 276.7422189.628
 281.0062189.788  286.772192.227 289.5332193.505 293.7972194.376 319.3992192.937
 354.3372192.994 519.4352197.348  533.532200.935 554.0962208.902 574.278 2219.45
#Mann= 3 , 0 , 0
       0      .1       0 262.894    .045       0  286.77      .1       0
Bank Sta=262.894,286.77
XS Rating Curve= 0 ,0
Exp/Cntr(USF)=0,0
Exp/Cntr=0.5,0.3

Type RM Length L Ch R = 1 ,750     ,10.7,10.7,10.7
XS GIS Cut Line= 4
2170411.96791694263942.6681727422170224.04016734263780.589221416
2170130.99778124263684.0205352712169924.73485027263830.054690395
#Sta/Elev= 30
       0 2290.35    26.1 2276.88    39.1 2267.23    47.7 2262.66      52 2261.42
    64.9 2260.14    69.4 2258.82      91  2246.8     104 2240.71   160.4 2220.73
   171.9 2215.44     195 2213.29   203.7 2210.58   235.5 2204.02   242.7 2201.43
   250.3 2197.64   256.4 2195.83   276.5 2192.72   284.7 2189.56   291.3  2190.1
   297.4 2192.78     302  2193.5   369.8 2191.21   491.3 2195.15   512.5 2195.12
   528.5  2196.6   576.7 2197.62   597.8 2203.42   612.9 2209.52     635 2220.19
#Mann= 3 , 0 , 0
       0      .1       0   276.5    .045       0   297.4      .1       0
Bank Sta=276.5,297.4
XS Rating Curve= 0 ,0
Exp/Cntr(USF)=0,0
Exp/Cntr=0.3,0.1

Type RM Length L Ch R = 1 ,591     ,149.7,149.7,149.7
XS GIS Cut Line= 3
2170438.07343211263571.1845008232170048.57133582263626.363964465
2169917.11437832263829.229639619
#Sta/Elev= 30
       0 2289.94    66.2 2255.91    72.8 2251.99    76.1 2250.59    82.7 2249.24
    92.7 2243.96   168.9 2212.29   178.8    2207   188.8 2205.63   195.5 2200.53
   205.3 2187.98     207 2186.79     207 2186.75   208.7 2185.63   215.3 2184.89
   225.2 2186.61     255 2187.74     265 2189.03   285.4 2188.15   331.3 2189.46
   367.7 2191.38   390.9 2191.29   497.3 2194.21   509.5 2194.93     521 2196.78
   549.5 2198.79   563.8 2198.96   592.2 2204.72   612.1  2211.9   635.1 2222.16
#Mann= 3 , 0 , 0
       0      .1       0     207    .045       0   225.2      .1       0
#XS Ineff= 2 , 0
                          267.16         2189.34
Permanent Ineff=
       F       F
Bank Sta=207,225.2
XS Rating Curve= 0 ,0
Exp/Cntr(USF)=0,0
Exp/Cntr=0.3,0.1

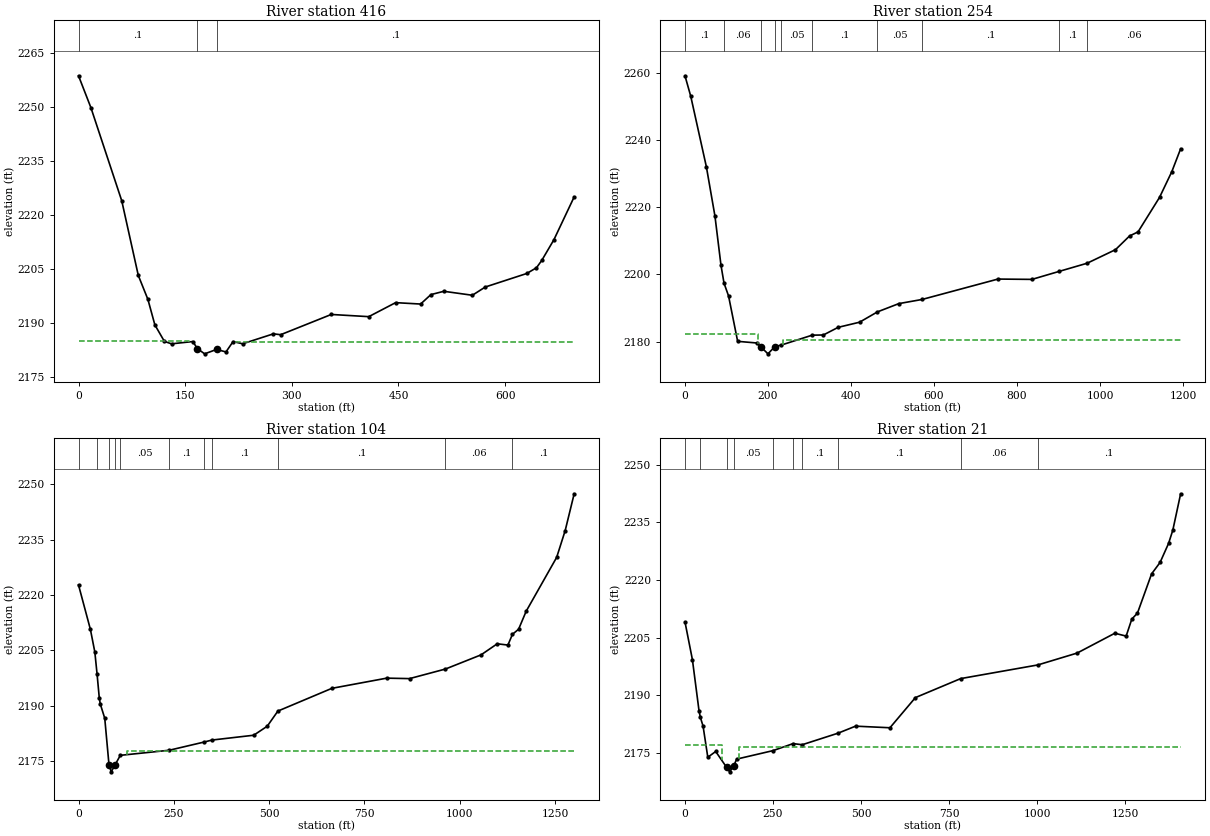
Type RM Length L Ch R = 1 ,416     ,162.1,162.1,162.1
XS GIS Cut Line= 3
2170360.17301285263400.7773336932170089.14447085 263449.46509573
2169905.75390051263829.229639619
#Sta/Elev= 30
       0 2258.63    17.4  2249.8    60.8 2223.94    84.1  2203.2    97.6 2196.56
   107.4 2189.48   120.8  2184.9   130.8 2184.23   160.8 2184.86   167.22182.896
   177.4 2181.45   194.1 2182.67   207.4 2181.98   217.4 2184.86   230.8 2184.24
   274.1    2187   284.3 2186.76   355.5 2192.38   408.2 2191.77     446 2195.66
   481.1 2195.27   495.6 2197.89   513.8 2198.81   553.9 2197.71   572.1    2200
   630.4 2203.75   644.1 2205.35   651.5 2207.37   668.7 2213.16   697.1 2225.01
#Mann= 3 , 0 , 0
       0      .1       0   167.2    .045       0   194.1      .1       0
#XS Ineff= 2 , 0
           155.9 2184.97  219.82         2184.83
Permanent Ineff=
       F       F
Bank Sta=167.2,194.1
XS Rating Curve= 0 ,0
Exp/Cntr(USF)=0,0
Exp/Cntr=0.3,0.1

Type RM Length L Ch R = 1 ,254     ,149.8,149.8,149.8
XS GIS Cut Line= 5
 2170371.9435286263358.5735999782170226.32498713263288.113015394
2170152.83809201 263273.879076642169932.48349447263535.550161224
2169603.92315664264056.133387354
#Sta/Elev= 30
       02259.088  13.9012252.997  51.5172232.037  72.2172217.361  86.7962202.683
  94.0852197.397 105.0192193.589 126.8882180.092  173.232179.593 183.2562178.386
 199.965 2176.37 216.6742178.534 231.1772178.949 306.4892181.923 333.5532181.984
 369.2062184.259 420.5812185.776 463.8432188.857 515.3142191.313 571.073 2192.54
 754.1452198.614 836.0692198.518 901.5712200.897 968.9872203.3231037.358 2207.36
1071.2612211.4351091.6722212.6481143.4212222.9011173.1452230.5881194.3122237.367
#Mann= 10 ,-1 , 0
       0      .1       0  94.085     .06       0 183.256    .045       0
 216.674     .06       0 231.177     .05       0 306.489      .1       0
 463.843     .05       0 571.073      .1       0 901.571      .1       0
 968.987     .06       0
#XS Ineff= 2 , 0
          175.76  2182.3  235.15          2180.5
Permanent Ineff=
       F       F
Bank Sta=183.256,216.674
XS Rating Curve= 0 ,0
Exp/Cntr(USF)=0,0
Exp/Cntr=0.5,0.3

Type RM Length L Ch R = 1 ,104     ,83.5,83.5,83.5
XS GIS Cut Line= 5
2170369.41187689263214.4706859772170318.04611073263182.129277653
 2170261.2437531263166.474697366  2170038.964362263356.822610032
2169532.34013204264085.786274936
#Sta/Elev= 30
       02222.763   31.182210.714  42.8112204.576  48.7482198.532  54.4422192.161
      572190.522  68.8192186.614   80.012173.937  85.8352172.096   95.222173.872
 109.657 2176.57 237.7882177.947 328.5352180.151 350.1932180.716 459.4442182.019
 494.9452184.459 522.912 2188.57 664.5172194.736 808.3042197.496 868.2682197.371
 962.4032199.9691055.8062203.8121098.2452206.8121126.2132206.4661138.1992209.394
 1154.182210.7481174.1572215.6471254.0652230.2361276.4322237.5041299.9892247.481
#Mann= 11 ,-1 , 0
       0      .1       0  48.748     .06       0   80.01    .045       0
   95.22     .06       0 109.657     .05       0 237.788      .1       0
 328.535     .05       0 350.193      .1       0 522.912      .1       0
 962.403     .06       01138.199      .1       0
#XS Ineff= 2 , 0
                          127.27         2177.79
Permanent Ineff=
       F       F
Bank Sta=80.01,95.22
XS Rating Curve= 0 ,0
Exp/Cntr(USF)=0,0
Exp/Cntr=0.5,0.3

Type RM Length L Ch R = 1 ,21      ,21,21,21
XS GIS Cut Line= 6
2170390.59970839263173.9627057622170327.69367461263090.165316565
2170249.76500324263103.5221344142170164.06385433263234.767020255
2170028.05726124263352.2386705822169517.46394183264076.045250962
#Sta/Elev= 30
       02209.076  21.0872199.257  40.0172185.855  43.8032184.214  51.3752181.958
  64.7822173.858  87.2072175.365 117.9312171.271 126.7762170.066 137.8222171.494
 146.7482173.379 249.9092175.586   306.8 2177.41 332.8762177.123 434.5292180.124
 484.2342181.953 581.8372181.535 654.1072189.385 782.5872194.3271001.7212197.883
1113.1552200.9691220.2232206.1291252.3432205.3831268.4032209.8021284.4632211.372
1324.6132221.5791348.7032224.5581372.7932229.5051384.8382232.9541407.0222242.419
#Mann= 10 ,-1 , 0
       0      .1       0  43.803     .06       0 117.931    .045       0
 137.822     .05       0 249.909      .1       0   306.8     .05       0
 332.876      .1       0 434.529      .1       0 782.587     .06       0
1001.721      .1       0
#XS Ineff= 2 , 0
          103.92 2177.15  153.03         2176.43
Permanent Ineff=
       F       F
Bank Sta=117.931,137.822
XS Rating Curve= 0 ,0
Exp/Cntr(USF)=0,0
Exp/Cntr=0.5,0.3
Stream Node=BIGCLEARCK      ,Main            , 0 , 0 ,Upstream end
Stream Node=BIGCLEARCK      ,Main            , 0 , 1 ,Downstream end
Stream Node=BROADRN         ,Main            , 0 , 0 ,Upstream end
Stream Node=BROADRN         ,Main            , 0 , 1 ,Downstream end
Stream Node=LAURELBR        ,Main            , 0 , 0 ,Upstream end
Stream Node=LAURELBR        ,Main            , 0 , 1 ,Downstream end
Stream Node=LAURELCK1       ,Main            , 0 , 0 ,Upstream end
Stream Node=LAURELCK1       ,Main            , 0 , 1 ,Downstream end
Stream Node=MEADOWRV3       ,Main            , 0 , 0 ,Upstream end
Stream Node=MEADOWRV3       ,Main            , 0 , 1 ,Downstream end
Stream Node=MEADOWRV4       ,Main            , 0 , 0 ,Upstream end
Stream Node=MEADOWRV4       ,Main            , 0 , 1 ,Downstream end
Stream Node=MLGNCK          ,Main            , 0 , 0 ,Upstream end
Stream Node=MLGNCK          ,Main            , 0 , 1 ,Downstream end
Stream Node=MLGNCKTR3       ,Main            , 0 , 0 ,Upstream end
Stream Node=MLGNCKTR3       ,Main            , 0 , 1 ,Downstream end
Stream Node=MLGNCKTR4       ,Main            , 0 , 0 ,Upstream end
Stream Node=MLGNCKTR4       ,Main            , 0 , 1 ,Downstream end
Stream Node=MUDDYCK         ,Main            , 0 , 0 ,Upstream end
Stream Node=MUDDYCK         ,Main            , 0 , 1 ,Downstream end
Stream Node=SECONDCK        ,Main            , 0 , 0 ,Upstream end
Stream Node=SECONDCK        ,Main            , 0 , 1 ,Downstream end
Stream Node=TUCKHORN        ,Main            , 0 , 0 ,Upstream end
Stream Node=TUCKHORN        ,Main            , 0 , 1 ,Downstream end
Stream Node=TUCKHORNT2      ,Main            , 0 , 0 ,Upstream end
Stream Node=TUCKHORNT2      ,Main            , 0 , 1 ,Downstream end
LCMann Table=0

Chan Stop Cuts=-1
Use User Specified Reach Order=0
Composite Channel Slope=5